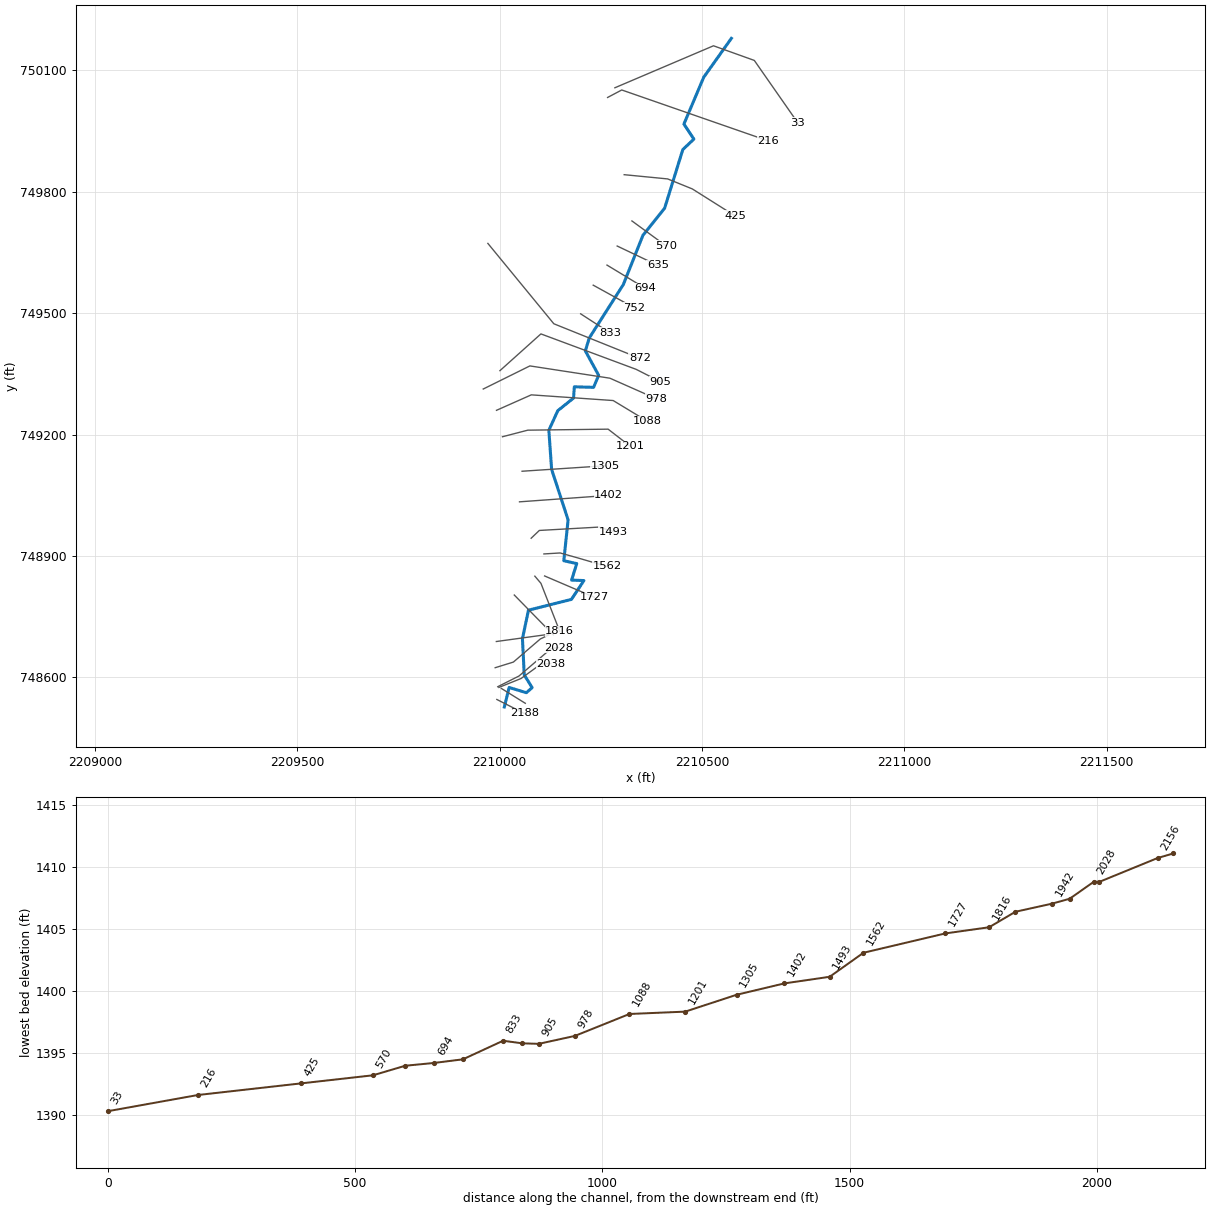
--- PECKSRNT1.prj (project) ---

Proj Title=PECKSRNT1
Current Plan=p01
Default Exp/Contr=0,0
English Units
Geom File=g01
Flow File=f01
Plan File=p01
BEGIN DESCRIPTION:
---------- MODELED AS PART OF WVEMD CTP PROGRAM, 2023----------
Stream Name: Pecks Run Tributary 1
Flood Zone:  AFH
Upshur County, WV
HEC-RAS Version: RAS 6.3
Vertical Datum: NAVD88
Projection: NAD 1983 StatePlane West Virginia S FIPS 4702 (US Feet)
Terrain: 1-meter LIDAR (FEMA Region III 3DEP collected 2016-2018)
Land Use: 2019 NLCD
Hydrologic Method:
WV SIR2010-5033 regression equations
Additional Model Notes:
None
END DESCRIPTION:
DSS File=dss
DSS Export Rating Curves= 0
DSS Export Rating Curve Sorted= 0
DSS Export Volume Flow Curves= 0
DXF OffsetX= 0
DXF OffsetY= 0
DXF ScaleX= 0
DXF ScaleY= 0

--- PECKSRNT1.p01 (plan) ---

Plan Title=Floodplain
Program Version=6.31
Short Identifier=Floodplain
Geom File=g01
Flow File=f01
Subcritical Flow
K Sum by GR= 0
Std Step Tol= 0.01
Critical Tol= 0.01
Num of Std Step Trials= 20
Max Error Tol= 0.3
Flow Tol Ratio= 0.001
Split Flow NTrial= 30
Split Flow Tol= 0.02
Split Flow Ratio= 0.02
Log Output Level= 0
Friction Slope Method= 1
Unsteady Friction Slope Method= 2
Unsteady Bridges Friction Slope Method= 1
Parabolic Critical Depth
Global Vel Dist= 0 , 0 , 0
Global Log Level= 0
CheckData=True
Encroach Param=-1 ,0,0, 0
Computation Interval=1MIN
Output Interval=1HOUR
Instantaneous Interval=1HOUR
Mapping Interval=1HOUR
Computation Time Step Use Courant=        0
Computation Time Step Use Time Series=    0
Computation Time Step Count To Double=0
Computation Time Step Max Doubling=0
Computation Time Step Max Halving=0
Computation Time Step Residence Courant=0
Run HTab= 0
Run UNet= 0
Run Sediment= 0
Run PostProcess= 0
Run WQNet= 0
Run RASMapper=-1
UNET Theta= 1
UNET Theta Warmup= 1
UNET ZTol= 0.02
UNET ZSATol= 0.02
UNET MxIter= 20
UNET Max Iter WO Improvement= 0
UNET MaxInSteps= 0
UNET DtIC= 0
UNET DtMin= 0
UNET MaxCRTS= 20
UNET WFStab= 2
UNET SFStab= 1
UNET WFX= 1
UNET SFX= 1
UNET Gravity=32.17405
UNET 1D Methodology=Finite Difference
UNET DSS MLevel= 4
UNET Pardiso=0
UNET DZMax Abort= 100
UNET Use Existing IB Tables=-1
UNET Froude Reduction=False
UNET Froude Limit= 0.8
UNET Froude Power= 4
UNET D1 Cores= 0
UNET WindReference=Eulerian
UNET WindDragFormulation=Hsu (1988)
UNET D2 Coriolis=0
UNET D2 Cores= 0
UNET D2 Theta= 1
UNET D2 Theta Warmup= 1
UNET D2 Z Tol= 0.01
UNET D2 Volume Tol= 0.01
UNET D2 Max Iterations= 20
UNET D2 Equation= 0
UNET D2 RampUpFraction=0.1
UNET D2 TimeSlices= 1
UNET D2 Turbulence Formulation=None
UNET D2 Eddy Viscosity=0.3
UNET D2 Transverse Eddy Viscosity=0.1
UNET D2 Smagorinsky Mixing=0.05
UNET D2 BCVolumeCheck=0
UNET D2 Cores=0
UNET D2 SolverType=PARDISO (Direct)
UNET D2 Minimum Iterations= 3
UNET D2 Maximum Iterations= 30
UNET D2 Restart Number= 10
UNET D2 Relaxation Coeff=1.3
UNET D2 SOR Precondition Iterations= 10
UNET D2 ILUT Maximum Fill= 8
UNET D2 ILUT Tolerance=1E-08
UNET D2 Convergence Tolerance=0.00001
UNET D1D2 MaxIter= 0
UNET D1D2 ZTol=0.01
UNET D1D2 QTol=0.1
UNET D1D2 MinQTol=1
Write IC File= 0
Write IC File at Fixed DateTime=0
Write IC File at Sim End=0
Echo Input=False
Echo Parameters=False
Echo Output=False
Write Detailed= 0
HDF Write Warmup=0
HDF Write Time Slices=0
HDF Flush=0
HDF Compression= 1
HDF Chunk Size= 1
HDF Spatial Parts= 1
HDF Use Max Rows=0
HDF Fixed Rows= 1
Calibration Method= 0
Calibration Iterations= 20
Calibration Max Change=0.05
Calibration Tolerance=0.2
Calibration Maximum=1.5
Calibration Minimum=0.5
Calibration Optimization Method= 1
WQ AD Non Conservative
WQ ULTIMATE=-1
WQ Max Comp Step=1HOUR
WQ Output Interval=15MIN
WQ Output Selected Increments= 0
WQ Create Restart=0
WQ Fixed Restart=0
WQ System Summary=0
WQ Write To DSS=0
Sorting and Armoring Iterations= 10
XS Update Threshold= 0.02
Bed Roughness Predictor= 0
Hydraulics Update Threshold= 0.02
Energy Slope Method= 1
Volume Change Method= 1
Sediment Retention Method= 0
Sediment TS Multiplier= 1
Warm Up Method= 0
XS Weighting Method= 0
Number of US Weighted Cross Sections= 1
Number of DS Weighted Cross Sections= 1
Upstream XS Weight=0
Main XS Weight=1
Downstream XS Weight=0
Number of DS XS's Weighted with US Boundary= 1
Upstream Boundary Weight= 1
Weight of XSs Associated with US Boundary= 0
Number of US XS's Weighted with DS Boundary= 1
Downstream Boundary Weight= 0.5
Weight of XSs Associated with DS Boundary= 0.5
Percentile Method= 0
Sediment Output Level= 3
Mass or Volume Output= 0
Output Increment Type= 1
Profile and TS Output Increment= 1
Transport Output Increment 1
XS Output Flag= 0
XS Output Increment= 10
Read HDF5 Sediment Hotstart= 0
Sediment Hotstart Type= 0
Write Gradation File= 0
Read Gradation Hotstart= 0
Write HDF5 File= 1
Write Binary Output= 1
Write DSS Sediment File= 0
DSS Sediment Output Type= 1
SV Curve= 0
Specific Gage Flag= 0
Subcell Erosion Methods= 0
Subcell Deposition Methods= 0
Advection Scheme= 1
Matrix Solver= 0
Implicit Weighting Factor= 1
Maximum Outer Loop Convergence Iterations= 5
Convergence Maximum Absolute= 0.001
Convergence RMSE= 0.0001
Grain Fractions Max Abs Error= 0.001
Max Subgrid Regions= 1
Max Subgrid Length Scale= 3.402823E+38
Initial Layer Thickness= 3.402823E+38
Min Layer Thickness= 3.402823E+38
Max Layer Thickness= 3.402823E+38
Number of Layers= 5

--- PECKSRNT1.f01 (steady flow) ---

Flow Title=Flows
Program Version=6.31
Number of Profiles= 1
Profile Names=01pct
River Rch & RM=PECKSRNT1,Main            ,2188
    91.3
River Rch & RM=PECKSRNT1,Main            ,1088
     133
Boundary for River Rch & Prof#=PECKSRNT1,Main            , 1
Up Type= 0
Dn Type= 3
Dn Slope=0.0072
DSS Import GetInterval= 0
DSS Import GetPeak= 0
DSS Import FillOption= 0

--- PECKSRNT1.g01 (geometry) ---

Geom Title=Geometry
Program Version=6.31

River Reach=PECKSRNT1       ,Main
Reach XY= 30
2210011.43663645748526.7901638752210023.34790762748574.864030898
2210065.84724857748562.0467693362210080.12955338748574.503139675
2210060.67537108748605.8952957242210056.17808634748695.391262323
2210071.06790841748765.9477504492210177.22300789748792.616378501
2210208.14335282748839.1673887072210177.69934969748840.341527388
2210190.40129182748881.093591899 2210158.4072075748888.237659305
2210169.04177167748989.0635498762210128.27158916749114.181601703
2210121.43783516749210.6506699322210143.49701686 749259.01896745
2210182.53948757749290.2658550292210184.44753097749318.054305017
2210232.07981421749316.8193939482210244.60088113749346.544671789
2210211.71426636749406.783512101  2210221.351208749438.808851644
2210305.61300004749570.9630000142210354.11426817749692.778795704
2210407.65058862749759.5723261682210452.60808717749904.543534696
 2210479.8935084749930.3629995882210455.30460401749967.519566208
2210504.30306622750083.310535282     2210572.633      750179.433

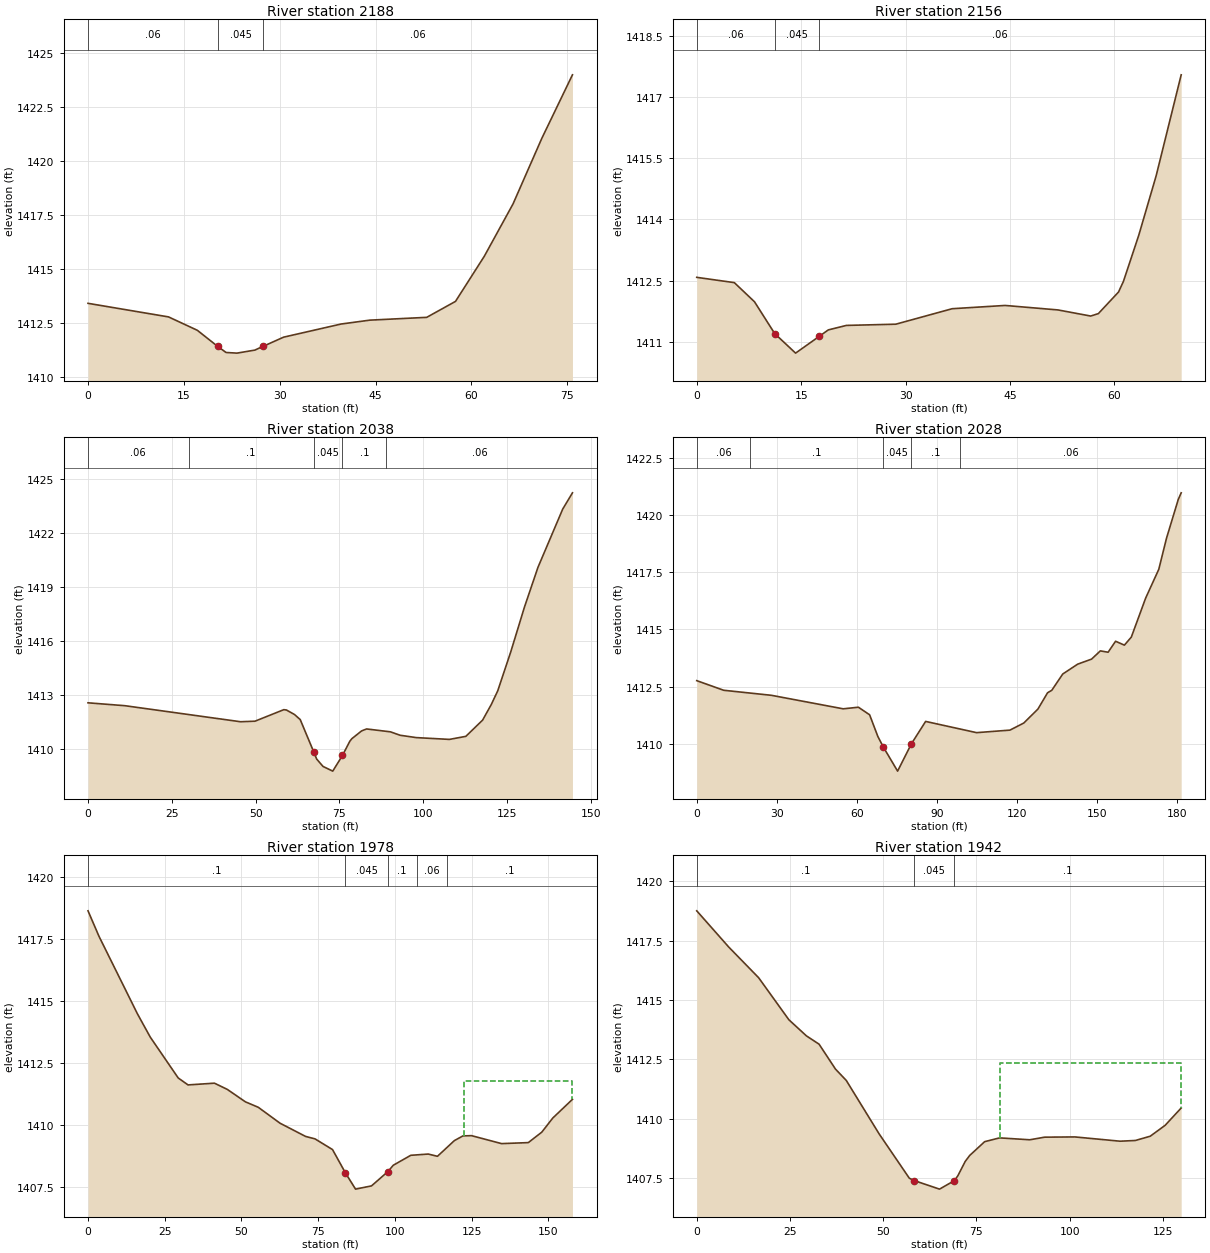
Type RM Length L Ch R = 1 ,2188    ,31.8,31.8,31.8
XS GIS Cut Line= 2
2209992.90499055748545.2588337732210060.42217295748510.895249899
#Sta/Elev= 17
       0  1413.4    12.6 1412.77    17.1 1412.15    20.3  1411.4    21.6 1411.12
    23.3 1411.09    26.1 1411.23   27.44 1411.41    30.6 1411.83    39.6 1412.44
    44.1 1412.62      53 1412.75    57.5 1413.49      62 1415.58    66.5 1418.01
      71 1421.05    75.8    1424
#Mann= 3 ,-1,0
       0     .06       0    20.3    .045       0   27.44     .06       0
Bank Sta=20.3,27.44
XS Rating Curve= 0 ,0
Exp/Cntr(USF)=0,0
Exp/Cntr=0.3,0.1

Type RM Length L Ch R = 1 ,2156    ,109.5,118.2,127.6
XS GIS Cut Line= 2
2210004.09356719748572.533764543 2210063.1920899748535.844387174
#Sta/Elev= 19
       0 1412.58     5.4 1412.45     8.3 1411.98    11.2  1411.2    14.2 1410.72
    17.61411.132    18.9 1411.29    21.5  1411.4    28.6 1411.43    36.7 1411.81
    44.3 1411.89    51.9 1411.78    56.6 1411.63    57.7 1411.69    60.6 1412.22
    61.3 1412.48    63.5 1413.61      66 1415.07    69.6 1417.55
#Mann= 3 ,-1,0
       0     .06       0    11.2    .045       0    17.6     .06       0
Bank Sta=11.2,17.6
XS Rating Curve= 0 ,0
Exp/Cntr(USF)=0,0
Exp/Cntr=0.3,0.1

Type RM Length L Ch R = 1 ,2038    ,8.9,10.7,11.4
XS GIS Cut Line= 4
2209997.98692902748575.0244733252210052.67826673748597.046206653
2210102.28766598748633.1037700132210126.48737294748633.829761222
#Sta/Elev= 30
       0 1412.58      11 1412.42    45.5 1411.53    49.8 1411.56    58.4  1412.2
    59.2 1412.18    61.6 1411.93    63.3 1411.65    67.3 1409.87    68.2 1409.46
    70.1 1409.05      73 1408.79    75.9 1409.66    78.1 1410.45    78.7 1410.59
    81.6 1411.02    83.1 1411.13    90.2 1410.97    93.1 1410.78    97.9 1410.65
   107.8 1410.55   112.7 1410.72   117.7 1411.62   120.3 1412.49   122.2 1413.24
   126.1 1415.41   130.2  1417.9   134.2 1420.09   141.6 1423.33   144.5 1424.23
#Mann= 5 ,-1,0
       0     .06       0      30      .1       0    67.3    .045       0
    75.9      .1       0   88.96     .06       0
Bank Sta=67.3,75.9
XS Rating Curve= 0 ,0
Exp/Cntr(USF)=0,0
Exp/Cntr=0.3,0.1

Type RM Length L Ch R = 1 ,2028    ,50.9,49.1,53.5
XS GIS Cut Line= 4
2209995.12501624748576.7875491662210047.62963468748603.238211232
2210126.80364654748670.8434894342210145.24573384748673.712258569
#Sta/Elev= 30
       0 1412.76    10.1 1412.34      28 1412.12    54.9 1411.53    60.6  1411.6
    64.8 1411.27    67.9 1410.32      70 1409.85    75.3 1408.81    80.4 1409.99
    85.8 1410.98   104.9 1410.49   117.4  1410.6   122.6 1410.91   127.9 1411.52
   131.5 1412.23   133.1 1412.34   137.2 1413.05   142.8 1413.48     148  1413.7
   151.3 1414.06   154.2    1414     157 1414.48   160.3 1414.31   162.9 1414.66
   168.3 1416.37   173.2 1417.62   176.1 1418.98   180.5 1420.67   181.6 1420.96
#Mann= 5 ,-1,0
       0     .06       0      20      .1       0      70    .045       0
    80.4      .1       0   98.79     .06       0
Bank Sta=70,80.4
XS Rating Curve= 0 ,0
Exp/Cntr(USF)=0,0
Exp/Cntr=0.3,0.1

Type RM Length L Ch R = 1 ,1978    ,40.3,36.1,28.2
XS GIS Cut Line= 4
2209988.77274172748623.7670985752210033.80249531748637.701714334
2210100.36998808748694.8182029222210121.27102035748704.653982815
#Sta/Elev= 30
       0 1418.62     3.6 1417.59    16.1 1414.48    20.3 1413.54    29.4  1411.9
    32.6 1411.62    41.2 1411.69    45.4 1411.44    51.3 1410.94    55.5 1410.72
    62.6 1410.08    70.9 1409.55      74 1409.45    79.7 1409.02    83.91408.083
    87.2 1407.43    92.4 1407.56    97.7 1408.13    99.5 1408.39   105.2 1408.79
   110.9 1408.84   113.9 1408.75   119.4 1409.38   122.2 1409.57     125 1409.58
   134.8 1409.26   143.5  1409.3   147.9 1409.72   151.5 1410.29   157.9 1411.04
#Mann= 5 ,-1,0
       0      .1       0    83.9    .045       0    97.7      .1       0
  107.14     .06       0  117.14      .1       0
#XS Ineff= 2 , 0
                          122.68         1411.79
Permanent Ineff=
       F       F
Bank Sta=83.9,97.7
XS Rating Curve= 0 ,0
Exp/Cntr(USF)=0,0
Exp/Cntr=0.3,0.1

Type RM Length L Ch R = 1 ,1942    ,79.9,73.6,65.6
XS GIS Cut Line= 2
2209991.69500521748688.521098936 2210120.4374462748706.186885012
#Sta/Elev= 26
       0 1418.76     8.6 1417.23    16.6 1415.94    24.7 1414.17    29.4 1413.49
    32.8 1413.14    37.2 1412.09    40.1 1411.61    48.9 1409.36      57 1407.49
   58.32 1407.39    65.1 1407.03    69.1 1407.39      70 1407.59      72  1408.2
    73.2 1408.45    77.2 1409.03    81.2 1409.19    89.3 1409.11    93.3 1409.22
   101.4 1409.23   113.5 1409.05   117.6 1409.08   121.6 1409.26   125.6 1409.72
   129.9 1410.45
#Mann= 3 ,-1,0
       0      .1       0   58.32    .045       0    69.1      .1       0
#XS Ineff= 2 , 0
                           81.32         1412.36
Permanent Ineff=
       F       F
Bank Sta=58.32,69.1
XS Rating Curve= 0 ,0
Exp/Cntr(USF)=0,0
Exp/Cntr=0.3,0.1

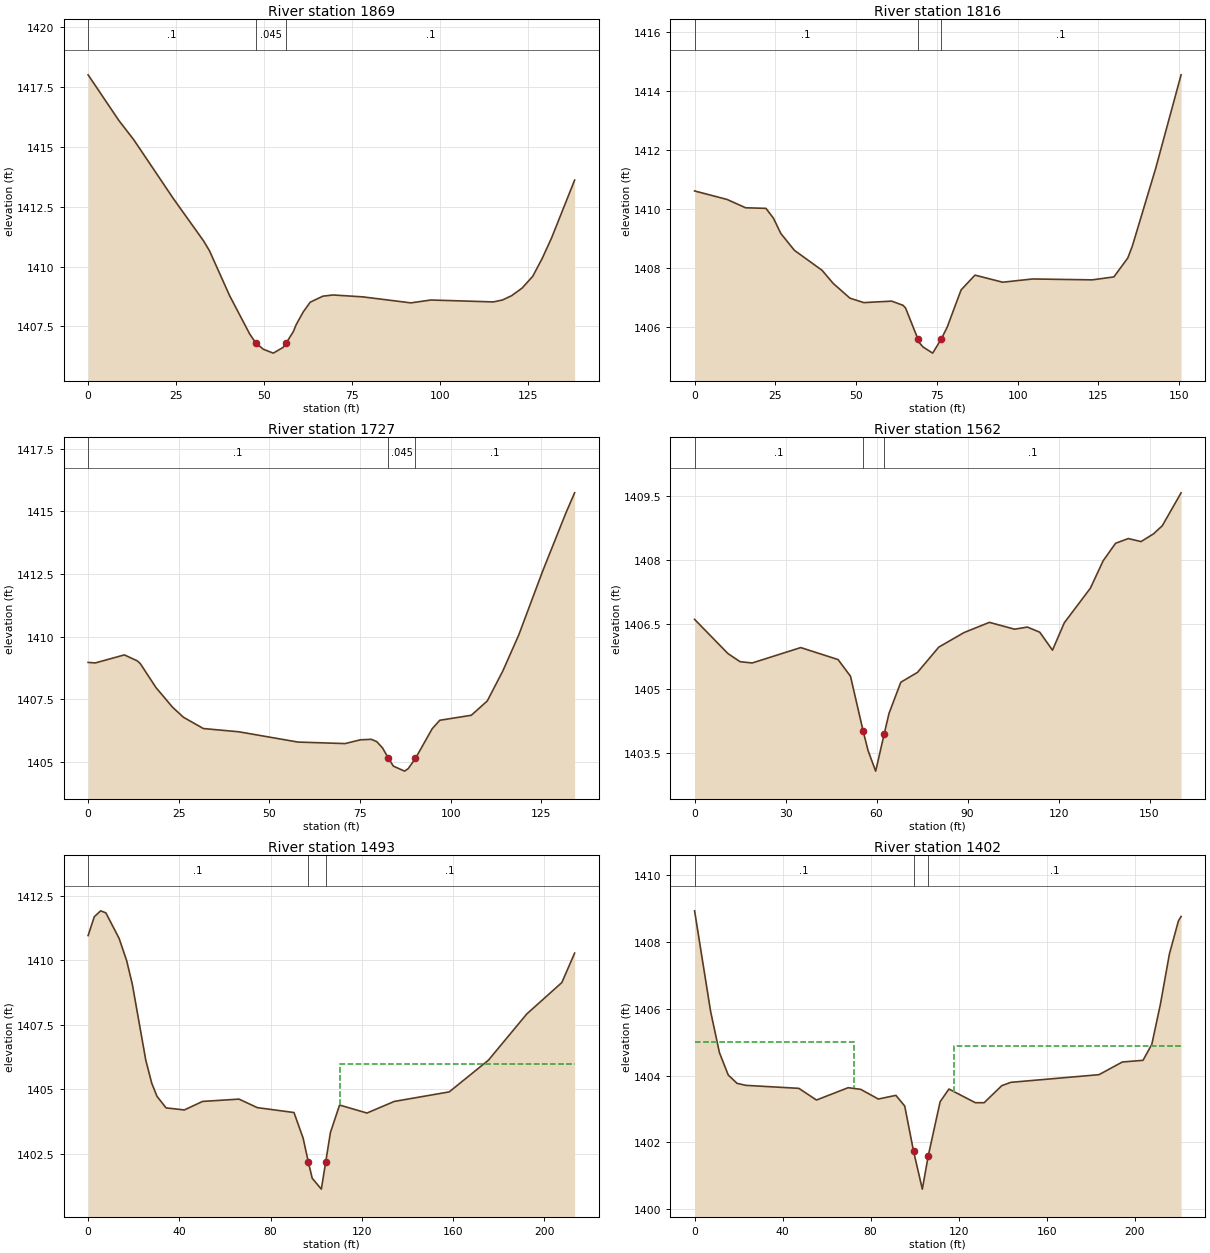
Type RM Length L Ch R = 1 ,1869    ,55.5,53.1,49.6
XS GIS Cut Line= 2
2210036.02759461748803.4216059032210132.74609689748704.653982815
#Sta/Elev= 30
       0 1418.01     8.7 1416.11      13 1415.29    24.3 1412.82    32.8 1411.07
    34.5 1410.65    40.2 1408.78    45.9 1407.18   47.62 1406.81    49.8 1406.54
    52.6 1406.38    55.4 1406.62    56.31406.809    58.3 1407.28    59.1 1407.57
    61.1  1408.1    63.1 1408.51    66.7 1408.76    69.6 1408.81    78.1 1408.73
    91.7 1408.48    97.4  1408.6   115.1 1408.52   117.7  1408.6   120.3 1408.78
   123.3  1409.1   126.3 1409.59     129 1410.34   131.7 1411.21   138.2 1413.61
#Mann= 3 ,-1,0
       0      .1       0   47.62    .045       0    56.3      .1       0
Bank Sta=47.62,56.3
XS Rating Curve= 0 ,0
Exp/Cntr(USF)=0,0
Exp/Cntr=0.3,0.1

Type RM Length L Ch R = 1 ,1816    ,83.9,88.8,94.4
XS GIS Cut Line= 3
2210086.83636905748850.0532674592210101.93222895748832.292429254
2210148.37039393748713.806748856
#Sta/Elev= 30
       0 1410.62    10.1 1410.33    15.8 1410.05    22.1 1410.03    24.4  1409.7
    26.7 1409.18    30.9 1408.61    39.5 1407.93    42.9 1407.49    48.1 1406.99
    52.4 1406.84      61 1406.89    64.5 1406.75    65.3 1406.66    69.11405.617
    69.6 1405.48    70.7 1405.34    73.7 1405.13    76.31405.595    78.2 1406.01
    82.5 1407.27    86.8 1407.77    95.4 1407.53   104.6 1407.64   123.1 1407.61
   129.8 1407.71   134.1 1408.35   135.5 1408.75   142.7 1411.37   150.6 1414.55
#Mann= 3 ,-1,0
       0      .1       0    69.1    .045       0    76.3      .1       0
Bank Sta=69.1,76.3
XS Rating Curve= 0 ,0
Exp/Cntr(USF)=0,0
Exp/Cntr=0.3,0.1

Type RM Length L Ch R = 1 ,1727    ,161.7,165.4,153.9
XS GIS Cut Line= 2
2210110.96734102748850.5360621412210234.36994986748797.714281236
#Sta/Elev= 30
       0 1408.97       2 1408.95      10 1409.27    13.6 1409.03    14.4 1408.92
    18.7 1407.97    23.3 1407.18    26.3 1406.78    31.8 1406.33    41.6  1406.2
    57.9 1405.79    70.9 1405.73    75.1 1405.88    78.1  1405.9    79.6 1405.81
    81.2 1405.56   82.82 1405.15    84.2 1404.83    87.3 1404.63    88.3 1404.73
    90.3 1405.14    94.9 1406.32      97 1406.66   105.7 1406.86   110.1 1407.43
   114.4 1408.63   118.8 1410.07   125.4 1412.62   131.8 1414.94   134.2 1415.74
#Mann= 3 ,-1,0
       0      .1       0   82.82    .045       0    90.3      .1       0
Bank Sta=82.82,90.3
XS Rating Curve= 0 ,0
Exp/Cntr(USF)=0,0
Exp/Cntr=0.3,0.1

Type RM Length L Ch R = 1 ,1562    ,65.8,68.3,70
XS GIS Cut Line= 4
2210109.24270515748904.9958820332210149.34195194748907.394982268
2210192.18302757748895.3994810932210264.84149183748874.150307581
#Sta/Elev= 30
       0 1406.62      11 1405.82      15 1405.63      19  1405.6      35 1405.96
    47.3 1405.68    51.4 1405.29    55.6    1404    57.2 1403.55    59.7 1403.07
    62.51403.934    64.1 1404.42      68 1405.15    73.5 1405.38    80.5 1405.97
    88.8 1406.31    97.2 1406.55   105.5 1406.39   109.7 1406.44   113.8 1406.32
     118  1405.9   121.9 1406.54   130.5 1407.35   134.7 1407.99   138.8  1408.4
     143 1408.51   147.2 1408.44   151.3 1408.62   154.2 1408.81   160.4 1409.58
#Mann= 3 ,-1,0
       0      .1       0    55.6    .045       0    62.5      .1       0
Bank Sta=55.6,62.5
XS Rating Curve= 0 ,0
Exp/Cntr(USF)=0,0
Exp/Cntr=0.3,0.1

Type RM Length L Ch R = 1 ,1493    ,89,91.3,89.5
XS GIS Cut Line= 4
 2210077.7119317748943.8038449732210097.96134355748963.057384112
2210245.35050525748971.3563233972210281.53388053748960.401723541
#Sta/Elev= 30
       0 1410.96     2.7 1411.69     5.5 1411.92     7.8 1411.84    13.6 1410.85
    16.9 1409.99    19.4 1409.07    25.3 1406.13    27.9 1405.24    30.2 1404.73
    34.2 1404.28    42.2  1404.2    50.2 1404.53    66.2 1404.62    74.2 1404.29
    90.3  1404.1    94.3 1403.11    96.61402.183    98.3 1401.55   102.3 1401.13
   104.21402.175   106.3 1403.33   110.3 1404.39   122.3 1404.08   134.3 1404.53
   158.4  1404.9   175.6 1406.13   192.4 1407.92   207.8 1409.14   213.4 1410.28
#Mann= 3 ,-1,0
       0      .1       0    96.6    .045       0   104.2      .1       0
#XS Ineff= 2 , 0
                          110.42            1406
Permanent Ineff=
       F       F
Bank Sta=96.6,104.2
XS Rating Curve= 0 ,0
Exp/Cntr(USF)=0,0
Exp/Cntr=0.3,0.1

Type RM Length L Ch R = 1 ,1402    ,94.4,96.8,94
XS GIS Cut Line= 2
2210048.89402215 749033.777810942210269.43538136749049.701374783
#Sta/Elev= 30
       0 1408.94     7.3 1405.92    11.3 1404.69    15.3 1404.02    19.3 1403.77
    23.3 1403.71    47.4 1403.62    55.4 1403.27    69.8 1403.64    75.5 1403.59
    83.5  1403.3    91.5 1403.41    95.5 1403.09    99.5 1401.74   103.5  1400.6
   106.2  1401.6   111.6 1403.22   115.6  1403.6   127.6 1403.19   131.6 1403.19
   139.6  1403.7   143.7  1403.8   183.8 1404.03   194.4 1404.41   203.8 1404.46
   207.8 1404.94   211.7 1406.14   215.8 1407.65   219.9 1408.64   221.1 1408.77
#Mann= 3 ,-1,0
       0      .1       0    99.5    .045       0   106.2      .1       0
#XS Ineff= 2 , 0
           72.54 1405.01  118.03          1404.9
Permanent Ineff=
       F       F
Bank Sta=99.5,106.2
XS Rating Curve= 0 ,0
Exp/Cntr(USF)=0,0
Exp/Cntr=0.3,0.1

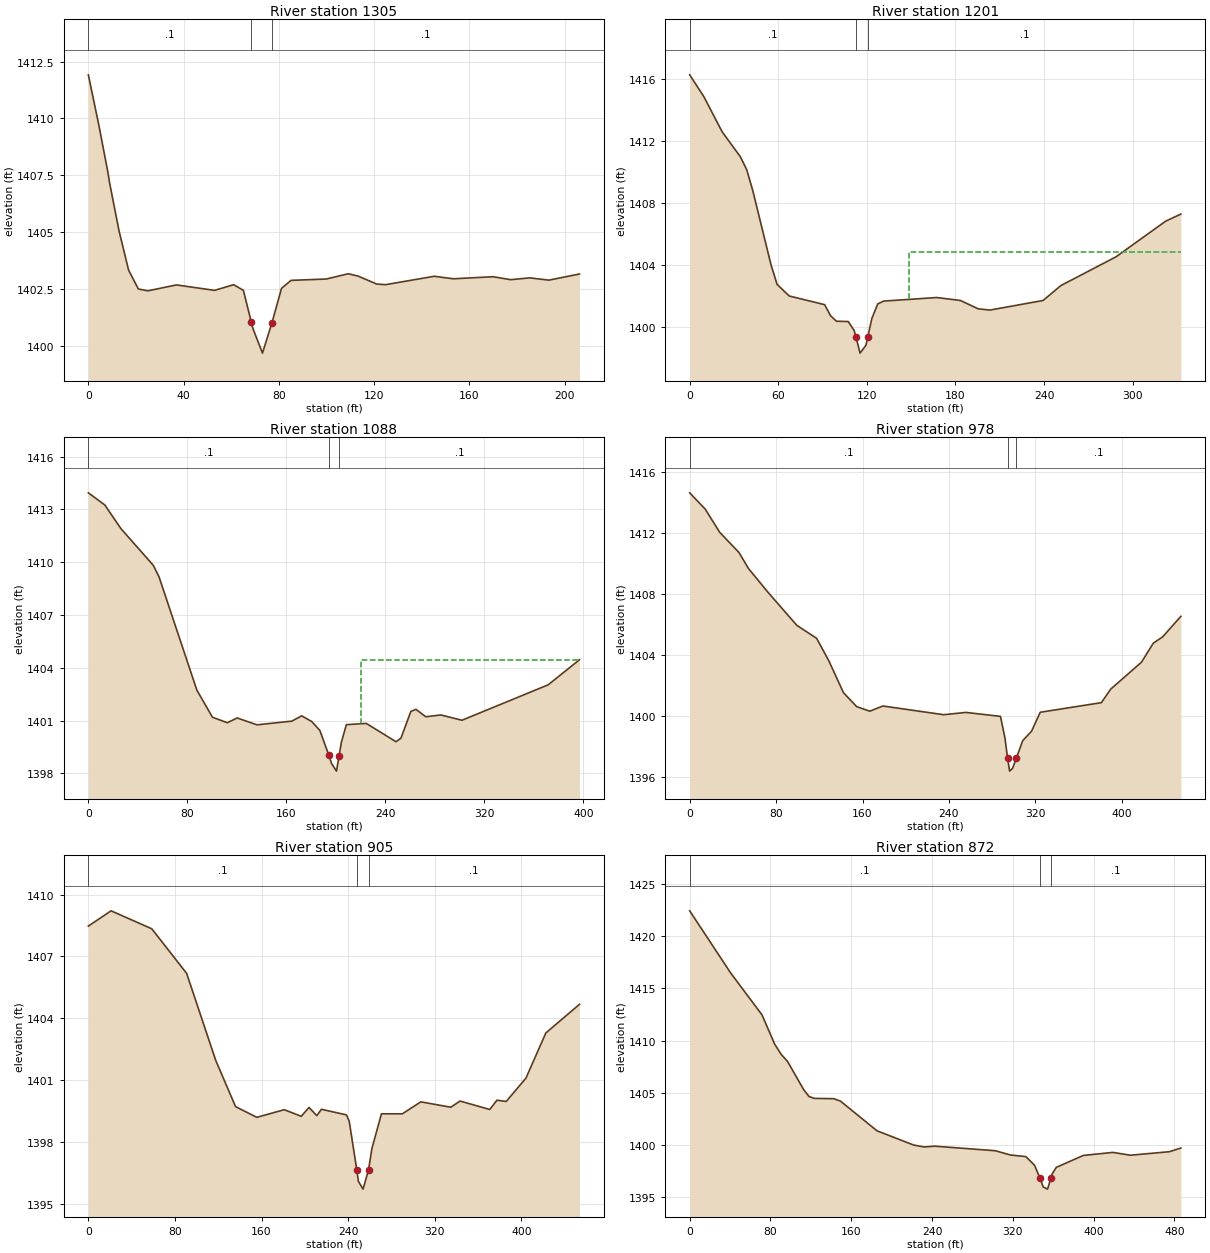
Type RM Length L Ch R = 1 ,1305    ,102.6,103.9,102.4
XS GIS Cut Line= 2
2210055.26344768749109.4147391912210261.05778497749122.970899774
#Sta/Elev= 30
       0 1411.92     4.4 1409.71     8.2 1407.64     8.9 1407.18    12.9 1405.05
    16.9 1403.33      21  1402.5      25 1402.42      37 1402.68      53 1402.44
      61 1402.69    65.1 1402.44    68.41401.049    69.1 1400.76    73.1 1399.68
    77.1 1401.02    81.1 1402.53    85.1 1402.88    99.9 1402.94   109.1 1403.17
   113.2 1403.07     121 1402.72   124.7 1402.69   145.2 1403.06   153.2 1402.95
   169.9 1403.04   177.3 1402.91   185.3 1402.99   193.3 1402.89   206.2 1403.16
#Mann= 3 ,-1,0
       0      .1       0    68.4    .045       0    77.1      .1       0
Bank Sta=68.4,77.1
XS Rating Curve= 0 ,0
Exp/Cntr(USF)=0,0
Exp/Cntr=0.3,0.1

Type RM Length L Ch R = 1 ,1201    ,111,112.7,110.6
XS GIS Cut Line= 4
2210006.84369183749194.6631999962210069.30736539749210.903755121
2210267.94184729749213.4023020632210322.90988002749170.927004045
#Sta/Elev= 30
       0 1416.29     9.6 1414.88      22 1412.61    34.4 1410.99    38.6 1410.17
    42.7 1408.83    55.1 1404.02    59.2 1402.76    67.4 1402.01    91.4 1401.45
    95.4 1400.74    99.4 1400.38   107.4 1400.36   111.4 1399.78  112.64 1399.36
   115.4 1398.32   119.4 1398.83   120.61399.348   123.4 1400.56   127.4  1401.5
   131.4 1401.68   167.4 1401.91   183.4 1401.72   195.4 1401.18   203.4  1401.1
   239.4 1401.72   251.4 1402.68   288.8 1404.54   322.4 1406.84   332.7  1407.3
#Mann= 3 ,-1,0
       0      .1       0  112.64    .045       0   120.6      .1       0
#XS Ineff= 2 , 0
                          148.28         1404.85
Permanent Ineff=
       F       F
Bank Sta=112.64,120.6
XS Rating Curve= 0 ,0
Exp/Cntr(USF)=0,0
Exp/Cntr=0.3,0.1

Type RM Length L Ch R = 1 ,1088    ,108,110.3,107.2
XS GIS Cut Line= 4
2209992.04066978749259.9821348422210078.05314826749298.209903057
2210280.43545058749284.155576508  2210365.885756749232.435654804
#Sta/Elev= 30
       0 1413.94    13.3 1413.25    26.4  1411.9    52.5 1409.82    57.1 1409.17
    87.7 1402.73   100.3 1401.19   112.3 1400.88   120.3 1401.15   136.3 1400.76
   164.4 1400.97   172.4 1401.27   180.5 1400.95   187.1 1400.44   194.4 1399.02
   196.5 1398.57   200.5 1398.13   202.61398.985   204.5 1399.78   208.5 1400.77
   224.6 1400.84   248.6  1399.8   252.6    1400   260.6 1401.52   264.7 1401.64
   272.7 1401.22   284.9 1401.32   301.9 1401.02   371.5 1403.03   396.9 1404.46
#Mann= 3 ,-1,0
       0      .1       0   194.4    .045       0   202.6      .1       0
#XS Ineff= 2 , 0
                          219.94         1404.45
Permanent Ineff=
       F       F
Bank Sta=194.4,202.6
XS Rating Curve= 0 ,0
Exp/Cntr(USF)=0,0
Exp/Cntr=0.3,0.1

Type RM Length L Ch R = 1 ,978     ,73.6,73.1,68.3
XS GIS Cut Line= 4
2209959.29474195749312.6166750912210074.59797177749369.739376101
2210272.27870015749339.3846606192210387.48482574749288.384320435
#Sta/Elev= 30
       0 1414.61    14.4 1413.54    27.8 1412.02    45.6  1410.7    54.5 1409.64
    72.7 1408.07    99.2 1405.92   117.5 1405.07   128.7 1403.61   142.4  1401.5
   154.6 1400.59   166.7 1400.29   178.8 1400.63   235.1 1400.06   255.7 1400.21
   287.7 1399.95   291.9 1398.52  294.27 1397.21   296.2 1396.36   298.9 1396.54
   302.5 1397.23   308.3 1398.36   316.5 1398.98   324.5 1400.22   381.1 1400.85
   389.8 1401.74   418.2  1403.5   429.2 1404.75   437.9 1405.17   454.7 1406.51
#Mann= 3 ,-1,0
       0      .1       0  294.27    .045       0   302.5      .1       0
Bank Sta=294.27,302.5
XS Rating Curve= 0 ,0
Exp/Cntr(USF)=0,0
Exp/Cntr=0.3,0.1

Type RM Length L Ch R = 1 ,905     ,33.1,33.3,33.6
XS GIS Cut Line= 4
2210000.56590069 749358.007163062210101.82465276749448.853966127
2210337.24547928749361.268827284 2210396.5471235749331.071601294
#Sta/Elev= 30
       0 1408.47      21 1409.21    58.6 1408.34    90.8 1406.18   117.7 1401.96
     136 1399.72   155.6  1399.2     181 1399.57   196.7 1399.25   203.9 1399.68
   211.1 1399.28   215.3 1399.59   238.4 1399.32     241 1399.02  248.02 1396.66
   249.5  1396.1   253.8 1395.72   258.9 1396.66     262 1397.69   270.8 1399.37
   290.1 1399.37   307.2 1399.95   334.9 1399.69   343.4 1399.99   370.9 1399.58
   377.5 1400.03   386.1 1399.97   404.3  1401.1   422.7 1403.29   453.8 1404.68
#Mann= 3 ,-1,0
       0      .1       0  248.02    .045       0   258.9      .1       0
Bank Sta=248.02,258.9
XS Rating Curve= 0 ,0
Exp/Cntr(USF)=0,0
Exp/Cntr=0.3,0.1

Type RM Length L Ch R = 1 ,872     ,40.1,38.8,37.2
XS GIS Cut Line= 3
2209970.72293857749672.5497686742210133.79534288749473.889226775
2210346.63048575749388.290257129
#Sta/Elev= 30
       0 1422.44    40.6 1416.48    71.6 1412.47    84.2 1409.65    90.6 1408.68
    96.9    1408     113 1405.28   118.2 1404.64   123.4 1404.46   142.7 1404.43
   149.3  1404.2   185.5 1401.35   221.7 1399.99   232.1  1399.8   242.4 1399.88
   302.7 1399.44   317.7 1399.03   332.9 1398.88   341.5 1398.05   346.6 1396.87
   350.1 1395.97   354.4 1395.76   357.8 1396.84   358.7 1397.18   363.1 1397.85
   389.8 1398.99   419.1 1399.28   436.4 1399.01   475.2 1399.35   486.4  1399.7
#Mann= 3 ,-1,0
       0      .1       0   346.6    .045       0   357.8      .1       0
Bank Sta=346.6,357.8
XS Rating Curve= 0 ,0
Exp/Cntr(USF)=0,0
Exp/Cntr=0.3,0.1

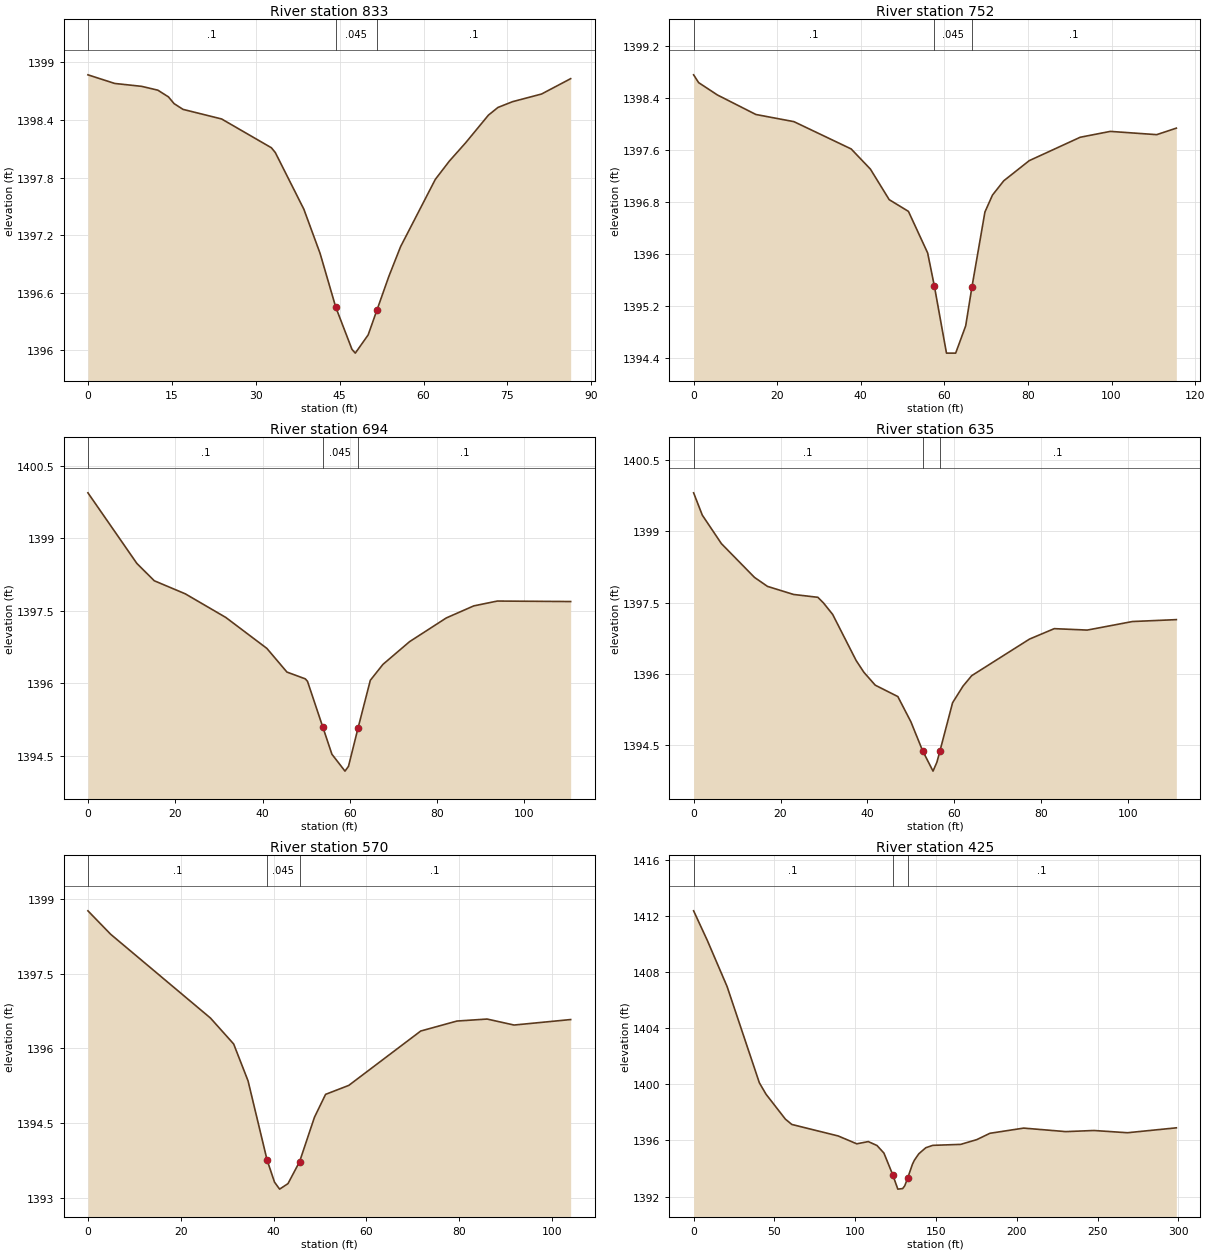
Type RM Length L Ch R = 1 ,833     ,80.5,81.3,81.6
XS GIS Cut Line= 2
2210200.10702736 749498.447797552210272.55924284749451.473284216
#Sta/Elev= 27
       0 1398.87     4.8 1398.78     9.6 1398.75    12.5 1398.71    14.4 1398.64
    15.4 1398.57      17 1398.51    23.9 1398.41    32.8 1398.11    33.5 1398.06
    38.6 1397.47    41.5 1397.01    44.3 1396.45    47.2 1396.01    47.8 1395.97
    50.1 1396.16    51.71396.424    53.8 1396.77    55.9 1397.08    62.1 1397.78
    64.6 1397.97    67.5 1398.16    71.6 1398.45    73.3 1398.53    75.9 1398.59
    81.1 1398.67    86.3 1398.83
#Mann= 3 ,-1,0
       0      .1       0    44.3    .045       0    51.7      .1       0
Bank Sta=44.3,51.7
XS Rating Curve= 0 ,0
Exp/Cntr(USF)=0,0
Exp/Cntr=0.3,0.1

Type RM Length L Ch R = 1 ,752     ,58,57.7,57.3
XS GIS Cut Line= 2
2210231.15797685749569.3076566482210332.27260725  749513.5751832
#Sta/Elev= 23
       0 1398.75     1.2 1398.63     5.7 1398.44    14.9 1398.14      24 1398.03
    37.7 1397.61    42.3  1397.3    46.8 1396.83    51.4 1396.65      56 1396.01
    57.61395.502    60.5 1394.47    62.7 1394.47    65.1 1394.89    66.6 1395.49
    69.7 1396.64    71.5  1396.9    74.2 1397.12    80.3 1397.43    92.5 1397.79
    99.7 1397.88   110.8 1397.83   115.5 1397.93
#Mann= 3 ,-1,0
       0      .1       0    57.6    .045       0    66.6      .1       0
Bank Sta=57.6,66.6
XS Rating Curve= 0 ,0
Exp/Cntr(USF)=0,0
Exp/Cntr=0.3,0.1

Type RM Length L Ch R = 1 ,694     ,58.5,59.1,60
XS GIS Cut Line= 2
2210265.14004378749618.976133027  2210359.726013749561.651303195
#Sta/Elev= 21
       0 1399.94    11.2 1398.48    15.2 1398.12    22.3 1397.85    31.6 1397.36
      41 1396.72    45.6 1396.23    49.8 1396.09    50.3 1396.04    53.81395.096
    55.9 1394.53    58.9 1394.18    59.7 1394.28    61.91395.076    64.7 1396.06
    67.6 1396.39    73.7 1396.86    82.1 1397.35    88.4  1397.6    93.8  1397.7
   110.6 1397.69
#Mann= 3 ,-1,0
       0      .1       0    53.8    .045       0    61.9      .1       0
Bank Sta=53.8,61.9
XS Rating Curve= 0 ,0
Exp/Cntr(USF)=0,0
Exp/Cntr=0.3,0.1

Type RM Length L Ch R = 1 ,635     ,66.7,65,63.8
XS GIS Cut Line= 2
2210290.39363435749666.0433069892210390.71208655749618.272615463
#Sta/Elev= 26
       0 1399.81       2 1399.34     6.4 1398.74      14 1398.03      17 1397.84
      23 1397.67    28.6 1397.61    29.9 1397.49      32 1397.25    37.4 1396.28
    39.2 1396.03    41.8 1395.76      47 1395.52      50 1394.99    52.7 1394.38
    55.1 1393.95      56 1394.14    56.71394.377    59.6 1395.39      62 1395.74
      64 1395.96    77.3 1396.73      83 1396.95    90.6 1396.92     101  1397.1
   111.1 1397.14
#Mann= 3 ,-1,0
       0      .1       0    52.7    .045       0    56.7      .1       0
Bank Sta=52.7,56.7
XS Rating Curve= 0 ,0
Exp/Cntr(USF)=0,0
Exp/Cntr=0.3,0.1

Type RM Length L Ch R = 1 ,570     ,142.5,144.9,146.2
XS GIS Cut Line= 2
2210326.82683288 749728.066888422210410.79337737749666.736486104
#Sta/Elev= 18
       0 1398.76     4.9 1398.29    26.4 1396.61    31.4 1396.09    34.5 1395.35
    38.61393.763    40.2 1393.32    41.3 1393.18    43.1 1393.29    45.6 1393.73
    48.8 1394.62    51.2 1395.08    56.2 1395.26    71.7 1396.35    79.5 1396.55
      86 1396.59    91.8 1396.47     104 1396.58
#Mann= 3 ,-1,0
       0      .1       0    38.6    .045       0    45.6      .1       0
Bank Sta=38.6,45.6
XS Rating Curve= 0 ,0
Exp/Cntr(USF)=0,0
Exp/Cntr=0.3,0.1

Type RM Length L Ch R = 1 ,425     ,204.1,209.1,203.5
XS GIS Cut Line= 4
2210307.62051009749842.4106860622210415.20159699749831.938190877
2210476.13247807749807.1850204392210581.80947494 749740.54186926
#Sta/Elev= 30
       0 1412.37     8.6 1410.23    20.7 1406.98    40.7 1400.11    44.8  1399.3
    56.8 1397.52    60.8 1397.14    89.5 1396.32     101 1395.76   108.1 1395.92
   113.5 1395.64   117.8  1395.1   123.2 1393.57   126.4 1392.53   129.4 1392.57
   130.7 1392.77   132.4 1393.29   135.5 1394.32   136.7  1394.6   139.4 1395.05
   143.7 1395.48     148 1395.65   165.3 1395.72   175.3 1396.06   183.4 1396.51
   204.3 1396.88   230.4 1396.63   247.8 1396.71   268.5 1396.55   298.8  1396.9
#Mann= 3 ,-1,0
       0      .1       0   123.2    .045       0   132.4      .1       0
Bank Sta=123.2,132.4
XS Rating Curve= 0 ,0
Exp/Cntr(USF)=0,0
Exp/Cntr=0.3,0.1

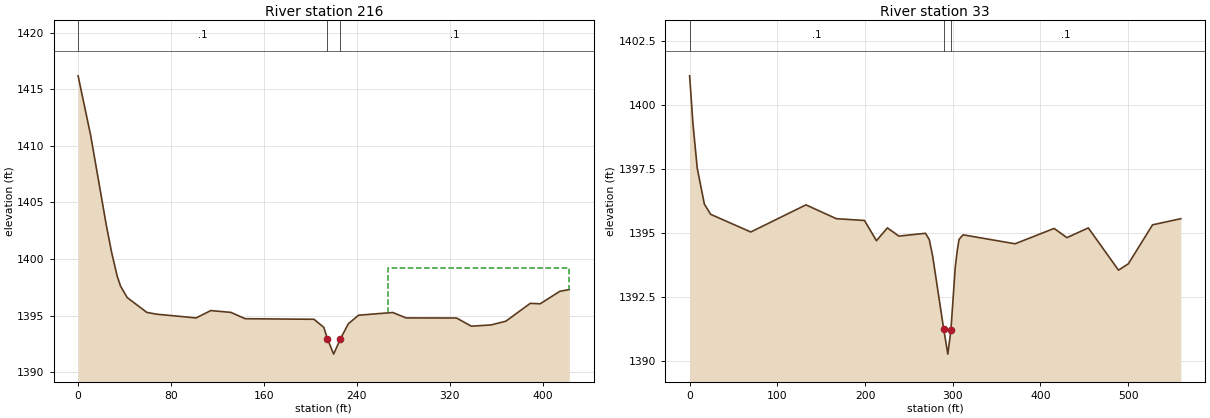
Type RM Length L Ch R = 1 ,216     ,182.5,182.5,182.5
XS GIS Cut Line= 3
2210266.64925699 750033.256052792210301.66743629750051.792551865
2210663.90315413749925.867964891
#Sta/Elev= 30
       0 1416.19    10.8 1410.94    24.4 1402.93    28.9 1400.57    33.6 1398.51
    36.6 1397.59    42.3 1396.59    59.2 1395.28    67.7 1395.12   101.6 1394.79
   114.3 1395.44   131.6 1395.28   143.9 1394.72   203.2 1394.67   211.7 1393.95
   214.7 1392.96   220.1 1391.59   225.9 1392.93   232.8 1394.28   241.6 1395.03
     271 1395.27   282.5 1394.79     326 1394.78   338.7 1394.06   355.7 1394.17
   368.4  1394.5   389.5 1396.08     398 1396.04   414.9 1397.14   423.1  1397.3
#Mann= 3 ,-1,0
       0      .1       0   214.7    .045       0   225.9      .1       0
#XS Ineff= 2 , 0
                          267.31         1399.18
Permanent Ineff=
       F       F
Bank Sta=214.7,225.9
XS Rating Curve= 0 ,0
Exp/Cntr(USF)=0,0
Exp/Cntr=0.3,0.1

Type RM Length L Ch R = 1 ,33      ,,,
XS GIS Cut Line= 4
2210284.67439028750057.246883693 2210528.3979146750161.019790529
2210629.31468638750124.8420798892210736.89577328 749970.61078716
#Sta/Elev= 30
       0 1401.15     3.8 1399.27     8.7 1397.54    16.8 1396.14      24 1395.74
    69.7 1395.05   132.6 1396.11   167.3 1395.57   199.4  1395.5     213 1394.71
   225.5 1395.21   238.6 1394.89   268.9    1395   273.2 1394.76   277.1 1394.11
   289.6 1391.28   294.4 1390.28   297.9 1391.21   302.9 1393.69   305.3 1394.36
   307.2 1394.76   311.8 1394.94   371.1 1394.59   415.6 1395.19   430.2 1394.83
   454.6 1395.21     489 1393.56   500.3 1393.81   527.8 1395.33   560.1 1395.57
#Mann= 3 ,-1,0
       0      .1       0   289.6    .045       0   297.9      .1       0
Bank Sta=289.6,297.9
XS Rating Curve= 0 ,0
Exp/Cntr(USF)=0,0
Exp/Cntr=0.3,0.1
LCMann Table=0

Chan Stop Cuts=-1
Use User Specified Reach Order=0
Composite Channel Slope=5